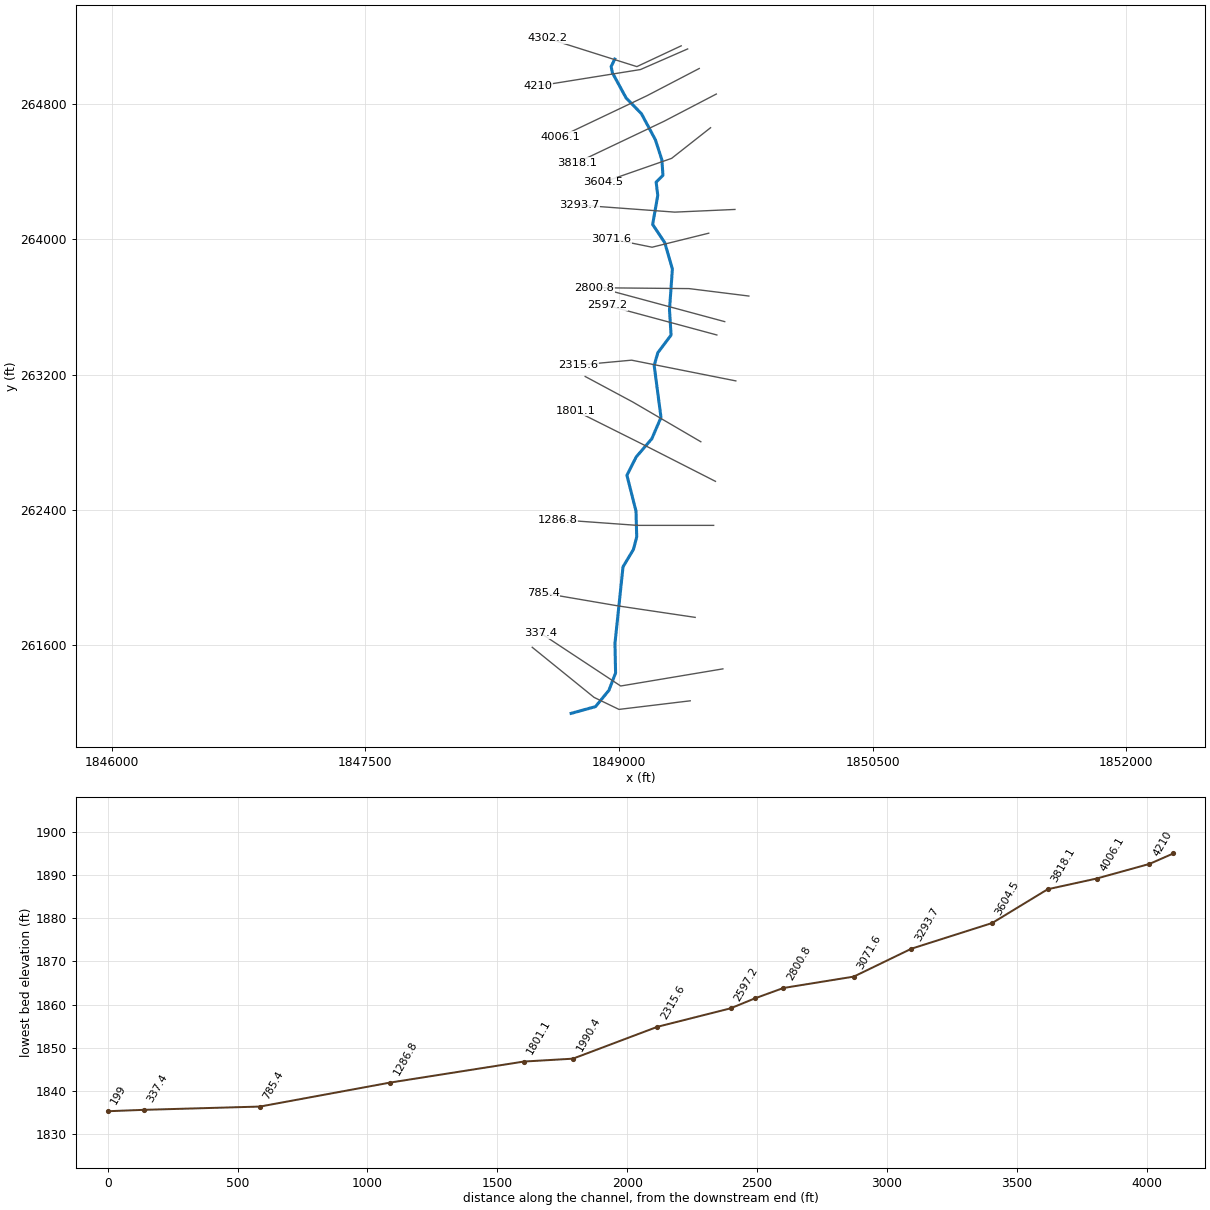
--- FranksFk.prj (project) ---

Proj Title=FranksFk
Current Plan=p01
Default Exp/Contr=0,0
English Units
Geom File=g01
Flow File=f01
Plan File=p01
BEGIN DESCRIPTION:
END DESCRIPTION:
DSS Export Rating Curves= 0
DSS Export Rating Curve Sorted= 0
DSS Export Volume Flow Curves= 0
DXF OffsetX= 0
DXF OffsetY= 0
DXF ScaleX= 0
DXF ScaleY= 0

--- FranksFk.p01 (plan) ---

Plan Title=Floodplain
Program Version=4.00
Geom File=g01
Flow File=f01
K Sum by GR=0
Std Step Tol=0.01
Critical Tol=0.01
Num of Std Step Trials=20
Max Error Tol=0.3
Flow Tol Ratio=0.001
Split Flow NTrial=30
Split Flow Tol=0.02
Split Flow Ratio=0.02
Log Output Level=0
Friction Slope Method=1
Unsteady Friction Slope Method=2
Unsteady Bridges Friction Slope Method=1
Global Log Level=0
CheckData=False
Run HTab=0
Run UNet=0
Run PostProcess=0
UNET Theta=0
UNET Theta Warmup=0
UNET ZTol=0
UNET ZSATol=0
UNET MxIter=0
UNET MaxInSteps=0
UNET DtIC=0
UNET DtMin=0
UNET MaxCRTS=0
UNET WFStab=0
UNET SFStab=0
UNET WFX=0
UNET SFX=0
UNET DSS MLevel=0
UNET DZMax Abort=0
UNET Convert EG Bridges=0
UNET Use Existing IB Tables=0
UNET Froude Limit=0
UNET Froude Power=0
Write IC File=0
Echo Input=False
Echo Output=False
Write Detailed=0

--- FranksFk.f01 (steady flow) ---

Flow Title=NFF Regression Equation
Program Version=4.00
Number of Profiles=1
Profile Names=P100yr
River Rch & RM=FranksFk,Main      ,4302.2
532.5970
River Rch & RM=FranksFk,Main      ,3293.7
567.9332
River Rch & RM=FranksFk,Main      ,2800.8
769.0784
River Rch & RM=FranksFk,Main      ,199
841.0084
Boundary for River Rch & Prof#=FranksFk,Main      ,1
Up Type=0
Dn Type=3
Dn Slope=0.004669

--- FranksFk.g01 (geometry) ---

Geom Title=USGS 10m DEM
Program Version=4.00

River Reach=FranksFk        ,Main
Reach XY= 30
     1848974.727      265065.364     1848953.363      265021.377
     1848960.606      264984.705     1849041.648      264835.751
     1849132.651      264742.032     1849215.051      264588.098
     1849253.082      264470.383     1849259.873      264378.022
     1849219.559      264337.281     1849229.086       264258.95
     1849198.752      264087.358     1849270.286      263980.057
     1849315.561      263824.312     1849298.356      263582.544
     1849307.864      263433.137     1849229.539      263329.458
     1849207.807      263253.849     1849248.102      262946.433
     1849193.772      262820.117     1849101.562      262712.811
     1849046.682       262604.27     1849100.271       262392.35
     1849104.576      262240.181     1849085.112      262165.443
      1849023.51       262062.78     1848975.947      261610.319
     1848979.622      261435.613     1848940.233      261332.839
     1848861.002      261236.404     1848716.714      261196.408

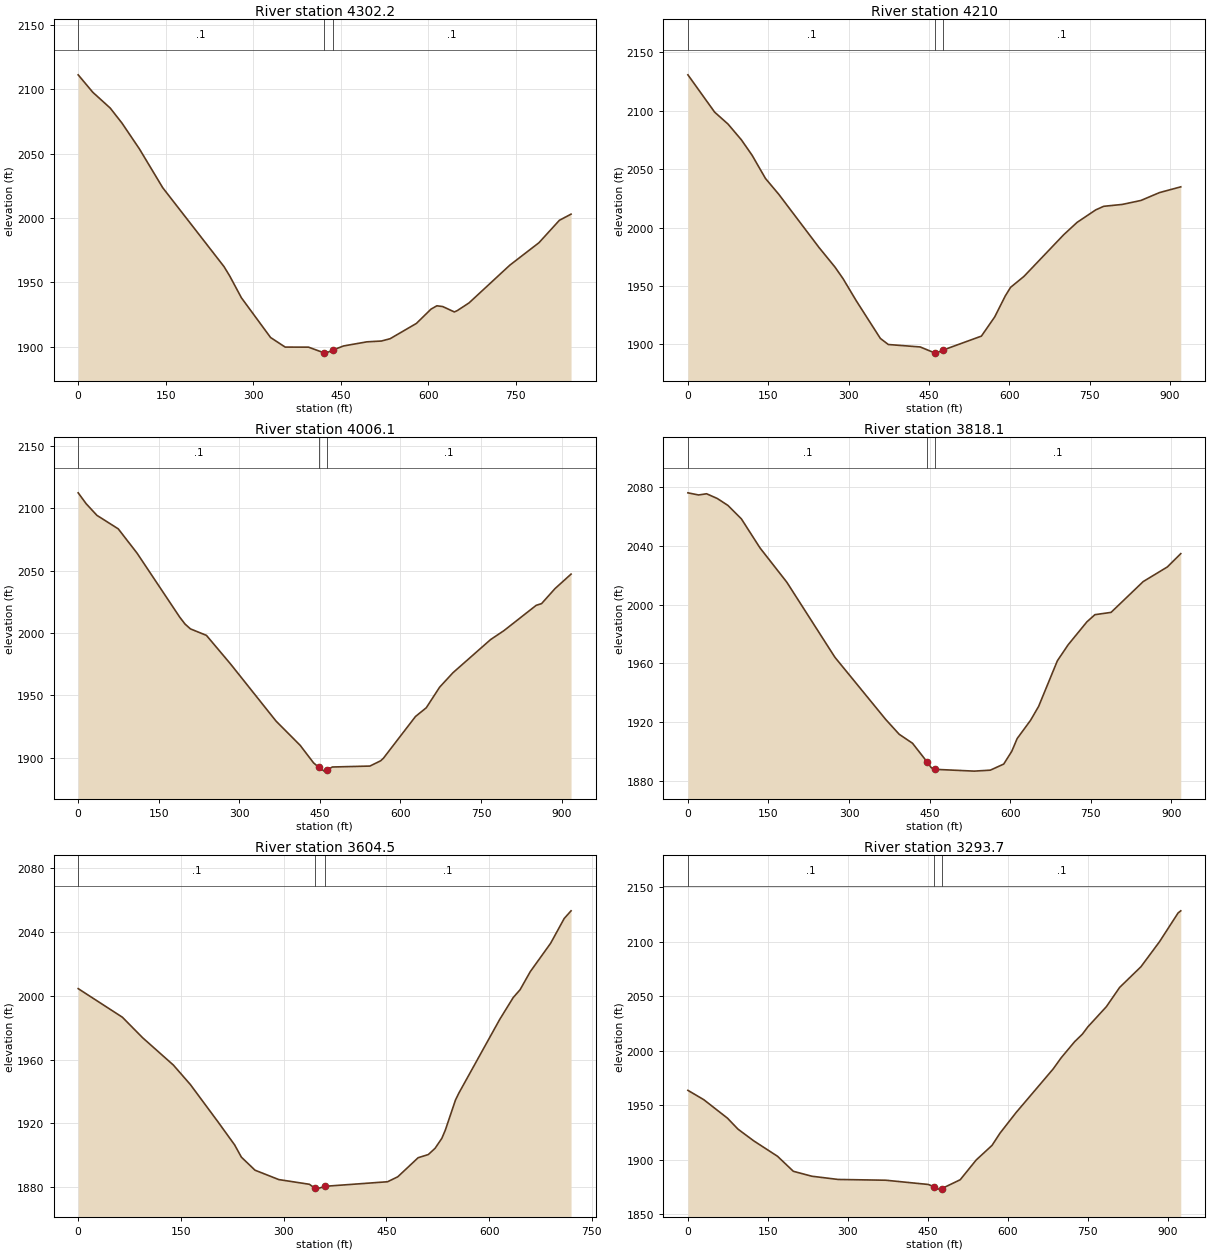
Type RM Length L Ch R = 1 ,4302.2  ,82.1,92.2,102.2
XS GIS Cut Line= 3
     1849367.659       265143.72     1849105.418      265020.795
     1848576.421      265188.029
#Sta/Elev= 30
       0 2111.22      25 2097.68    54.9 2085.38    74.9 2073.79   104.9 2053.65
   144.8 2023.52   249.7 1962.28   259.7 1954.85   279.6 1937.99   329.6  1907.1
   354.6 1899.65   394.6  1899.6   420.7 1895.27   424.6 1894.96   435.7 1897.28
   454.6 1900.53   494.6 1903.73   519.5 1904.36   534.5 1906.18   579.5 1918.06
   604.5 1929.16   614.5 1931.74   624.5 1931.16   644.5 1926.96   649.5 1928.02
   669.5 1933.94   739.5 1963.31   789.4 1980.75   824.4 1998.17   844.4 2002.96
#Mann= 3 , 0 , 0
       0      .1       0   420.7    .045       0   435.7      .1       0
Bank Sta=420.7,435.7
XS Rating Curve= 0 ,0
Exp/Cntr=0.3,0.1

Type RM Length L Ch R = 1 ,4210    ,196.9,203.9,210.9
XS GIS Cut Line= 3
     1849405.796      265125.357      1849126.64      265003.448
     1848519.084      264906.083
#Sta/Elev= 30
       0 2130.64    49.9 2098.72    74.9  2088.5    99.9 2074.97   119.8 2061.85
   144.8 2041.97   169.8 2028.32   244.7 1982.93   274.6  1966.1   289.6 1956.22
   314.5 1937.14   359.2 1905.11   374.1  1899.9   433.6 1897.81   460.5 1892.73
   463.4 1892.53   475.5 1895.02   547.8 1907.09   572.6 1923.48   592.4 1941.49
   602.3 1948.84   627.2 1958.16   701.6 1993.91   726.4  2004.4   761.1 2015.06
     776 2018.14   810.8 2019.76   845.5 2023.15   880.2 2029.88   919.9  2034.8
#Mann= 3 , 0 , 0
       0      .1       0   460.5    .045       0   475.5      .1       0
Bank Sta=460.5,475.5
XS Rating Curve= 0 ,0
Exp/Cntr=0.3,0.1

Type RM Length L Ch R = 1 ,4006.1  ,188,188,187.9
XS GIS Cut Line= 3
     1849474.427      265009.804     1849165.523      264848.842
     1848651.347      264604.396
#Sta/Elev= 30
       0 2112.29    14.9 2103.53    34.8 2094.26    74.6  2083.4   109.5 2063.99
   189.1 2012.58     199 2007.03     209 2003.19   238.8 1997.98   283.6 1975.08
   368.3 1929.29   413.2 1909.86   438.2 1895.76   448.2 1892.14   458.2 1889.14
   463.2 1890.08   473.2 1892.45   543.1  1893.2   563.1 1897.42   568.1 1899.39
     628 1932.96     648 1939.92   672.9 1956.44   697.9 1968.11   767.8 1994.62
   792.8 2001.84   852.7 2022.08   862.7 2023.45   887.7 2035.48   917.6 2047.11
#Mann= 3 , 0 , 0
       0      .1       0   448.2    .045       0   463.2      .1       0
Bank Sta=448.2,463.2
XS Rating Curve= 0 ,0
Exp/Cntr=0.3,0.1

Type RM Length L Ch R = 1 ,3818.1  ,216.1,213.6,211.1
XS GIS Cut Line= 3
     1849575.229      264858.633     1849266.326      264697.671
      1848752.15      264453.225
#Sta/Elev= 30
       0 2075.98    19.9 2074.52    34.8 2075.34    54.7 2072.13    74.6 2067.39
    99.5  2058.3   134.4 2038.43   184.1 2015.22   273.7 1964.12   368.3 1921.82
   393.3 1911.76   418.2 1905.62   445.1 1893.05   453.2 1888.94   460.1 1887.89
   533.1 1886.67   563.1 1887.33     588 1891.48     603 1900.19     613 1908.81
     638 1921.27     653 1930.74   687.9 1961.76   707.9  1972.6   742.9 1988.24
   757.8  1993.1   787.8 1994.65   847.7 2015.62   892.7 2025.57   917.6 2034.62
#Mann= 3 , 0 , 0
       0      .1       0   445.1    .045       0   460.1      .1       0
Bank Sta=445.1,460.1
XS Rating Curve= 0 ,0
Exp/Cntr=0.3,0.1

Type RM Length L Ch R = 1 ,3604.5  ,318.2,310.8,302.8
XS GIS Cut Line= 3
     1849541.213      264659.434     1849311.009      264478.317
     1848908.152      264337.825
#Sta/Elev= 30
       0 2004.41    64.5 1986.51    94.3 1973.57     139 1956.54   163.8 1944.34
   203.6 1921.29   228.4 1906.56   238.3 1898.87   258.2 1890.71   292.9 1884.84
   337.6 1881.89   345.1 1879.58   347.5 1878.86   360.1 1880.62   451.7 1883.48
   466.6 1886.58   496.3 1898.52   511.2 1900.51   521.1 1904.44     531 1910.71
     536 1915.78   550.9  1934.7   555.8    1939   615.4  1985.1   635.2 1998.85
   645.2 2003.75     660 2015.01   689.8 2032.84   709.6 2048.34   719.6 2053.13
#Mann= 3 , 0 , 0
       0      .1       0   345.1    .045       0   360.1      .1       0
Bank Sta=345.1,360.1
XS Rating Curve= 0 ,0
Exp/Cntr=0.3,0.1

Type RM Length L Ch R = 1 ,3293.7  ,214.4,222.1,229.9
XS GIS Cut Line= 3
     1849685.543      264176.249     1849329.628      264160.371
     1848762.599      264202.128
#Sta/Elev= 30
       0 1963.55    29.7 1955.02    74.2 1938.04      94 1927.95   123.7 1917.16
   168.2 1903.04   197.9 1889.27   232.6 1884.75     282 1881.79   371.2 1881.09
     451  1877.2   461.6 1875.16     471 1872.92   476.6 1873.48   510.9  1881.5
   540.8 1899.57   570.7 1913.07   585.7 1924.32   615.6 1943.05   685.4  1983.2
   700.4 1993.41   725.3    2008   740.3 2015.16   750.3  2021.7   785.2 2040.31
   810.1 2057.98     850  2076.9   884.9  2099.9   919.8 2126.31   924.8 2128.24
#Mann= 3 , 0 , 0
       0      .1       0   461.6    .045       0   476.6      .1       0
Bank Sta=461.6,476.6
XS Rating Curve= 0 ,0
Exp/Cntr=0.3,0.1

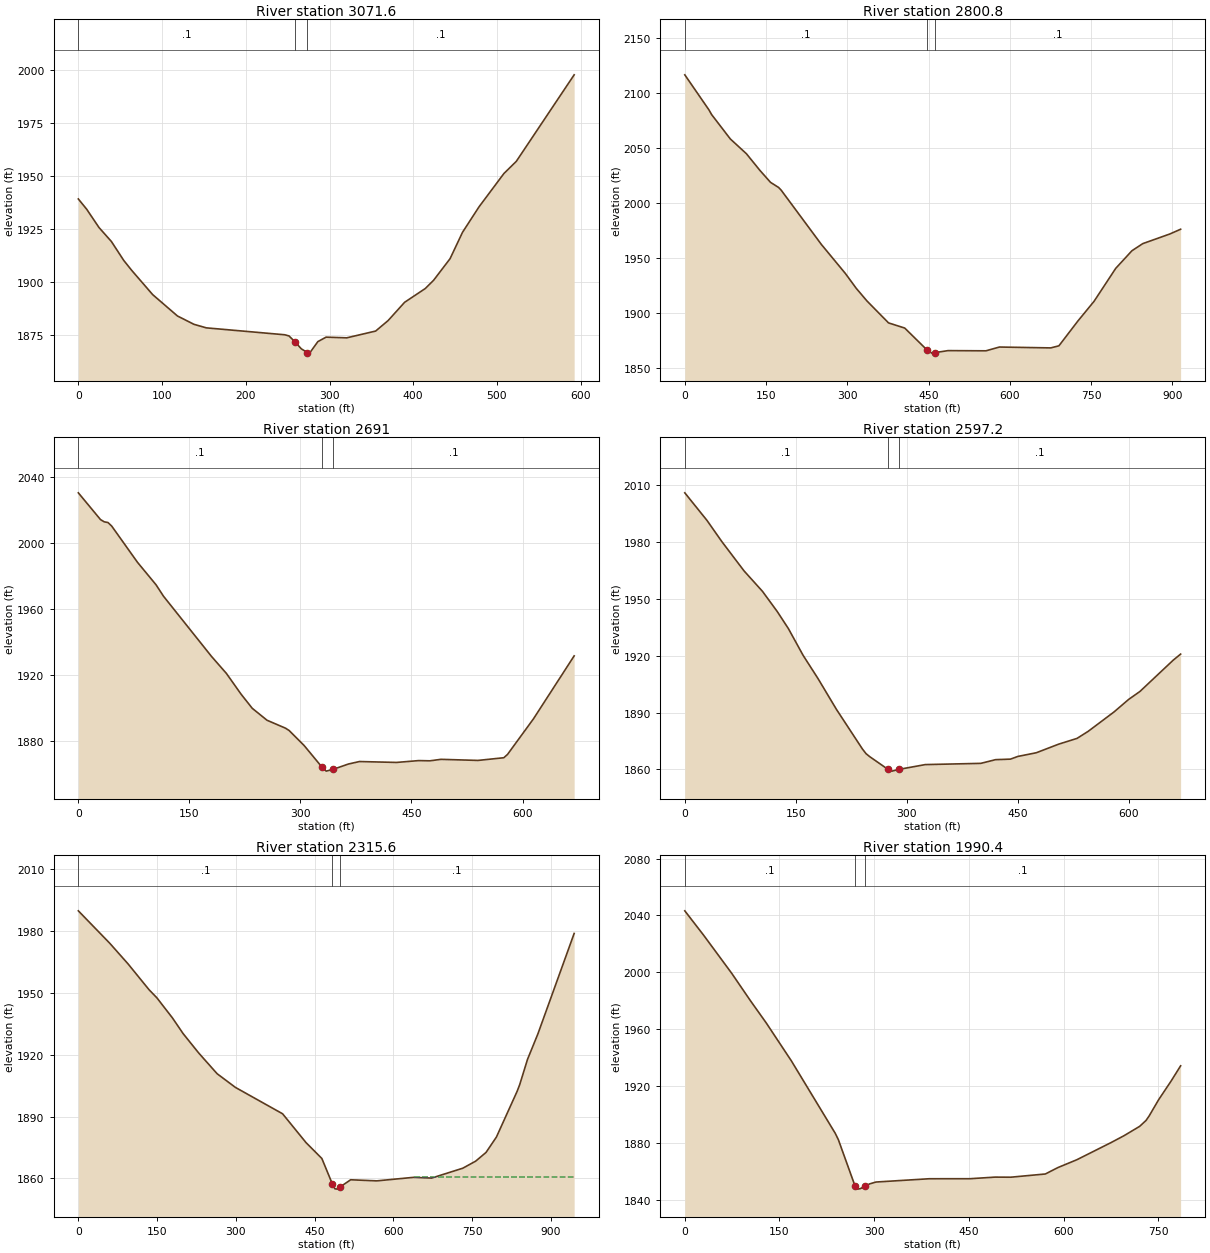
Type RM Length L Ch R = 1 ,3071.6  ,276.5,270.8,265
XS GIS Cut Line= 3
     1849530.539      264035.837     1849195.389      263952.895
     1848953.336      264001.983
#Sta/Elev= 30
       0 1939.13     9.9 1934.34    24.7 1925.66    39.5 1919.08    54.3 1910.13
    64.1 1905.31    88.8 1894.04   118.4 1883.97   138.1 1880.04   152.9 1878.37
   246.6 1875.11   251.6 1874.57   258.7 1871.82   266.3  1868.5   273.7  1866.7
   276.2 1866.46   286.1 1871.89   295.9 1873.99   320.6 1873.67   355.1 1876.86
     370 1881.81   389.7 1890.42   414.4 1896.92   424.3 1900.79     444 1910.98
   458.9 1923.45   478.6 1935.43   508.3 1951.13   523.1 1956.86   592.2 1997.65
#Mann= 3 , 0 , 0
       0      .1       0   258.7    .045       0   273.7      .1       0
Bank Sta=258.7,273.7
XS Rating Curve= 0 ,0
Exp/Cntr=0.3,0.1

Type RM Length L Ch R = 1 ,2800.8  ,115.6,109.8,104.1
XS GIS Cut Line= 3
     1849767.732      263664.184     1849414.262      263708.149
     1848854.972      263713.349
#Sta/Elev= 30
       0 2116.87    44.5 2085.07    49.5 2080.75    84.1 2058.55   113.8 2045.12
   138.5  2030.1   158.3  2019.1   173.2 2014.46   178.1 2011.91   252.3 1962.57
   296.8 1936.06   316.6 1922.71   336.4 1911.24   376.2 1891.31   406.1 1886.62
   446.9 1866.88   456.1 1863.83   461.9  1864.3     486 1866.11     556 1865.93
   580.9 1869.37   675.8 1868.58   690.8 1870.48   725.7 1892.95   755.7 1910.97
   795.7 1940.92   825.6 1956.92   845.6 1963.39   895.5 1972.14   915.5 1976.48
#Mann= 3 , 0 , 0
       0      .1       0   446.9    .045       0   461.9      .1       0
Bank Sta=446.9,461.9
XS Rating Curve= 0 ,0
Exp/Cntr=0.3,0.1

Type RM Length L Ch R = 1 ,2691    ,94.2,93.8,93.5
XS GIS Cut Line= 2
     1849624.952      263512.845     1848978.349       263687.19
#Sta/Elev= 30
       0  2030.2      30 2013.95      35 2012.62      40 2012.19      45 2010.08
      80 1988.01     105 1974.42     115 1967.52   179.9 1930.98   199.9 1920.74
   219.9 1908.05   234.9 1899.53   254.9 1892.28   279.9 1887.46   284.9    1886
   304.9 1877.01   329.2  1863.8   334.8 1861.43   344.2 1862.52   364.8 1865.74
   379.8 1867.25   429.8  1866.7   459.8 1867.82   474.8 1867.68   489.8 1868.58
   539.8 1867.92   574.7 1869.55   579.7 1871.56   614.7 1893.12   669.7 1931.32
#Mann= 3 , 0 , 0
       0      .1       0   329.2    .045       0   344.2      .1       0
Bank Sta=329.2,344.2
XS Rating Curve= 0 ,0
Exp/Cntr=0.3,0.1

Type RM Length L Ch R = 1 ,2597.2  ,279.7,281.6,283.5
XS GIS Cut Line= 2
     1849578.452      263433.935     1848931.849      263608.281
#Sta/Elev= 30
       0 2006.08      30  1991.5      50 1980.35      80 1964.87     105 1954.02
   124.9 1943.38   139.9  1934.4   159.9  1920.2   179.9 1908.02   204.9 1891.68
   239.9 1870.82   244.9  1868.3   249.9 1866.73     274 1860.17   279.9 1859.12
     289 1860.03   324.8 1862.57   399.8 1863.22   419.8 1865.18   439.8 1865.45
   449.8 1866.87   474.8 1868.83   504.8 1873.34   529.8 1876.41   544.8 1880.12
   579.7 1890.36   599.7 1897.05   614.7 1901.17   659.7 1917.72   669.7 1920.92
#Mann= 3 , 0 , 0
       0      .1       0     274    .045       0     289      .1       0
Bank Sta=274,289
XS Rating Curve= 0 ,0
Exp/Cntr=0.3,0.1

Type RM Length L Ch R = 1 ,2315.6  ,332.9,325.1,317.3
XS GIS Cut Line= 3
     1849690.594      263162.431     1849074.034       263284.98
     1848759.255      263255.875
#Sta/Elev= 30
       0 1989.65    59.9 1973.94    94.8 1963.93   134.7 1951.45   149.7 1947.51
   179.6 1937.68   199.6  1930.2   229.5 1920.74   264.4 1910.76   299.3 1904.12
   389.2 1891.34     434 1877.33     464 1869.69   483.7 1857.54   488.9    1855
   493.9 1854.85   498.7  1855.9   518.9 1859.38   568.8 1858.85   638.5 1860.55
   673.1  1860.2   732.4 1864.97     757 1868.39   776.8 1872.63   796.6 1880.08
   836.1 1902.25     841  1905.5   855.8 1917.68   875.6 1930.03   944.7  1978.7
#Mann= 3 , 0 , 0
       0      .1       0   483.7    .045       0   498.7      .1       0
#XS Ineff= 2 , 0
                          638.78         1860.58
Permanent Ineff=
       F       F
Bank Sta=483.7,498.7
XS Rating Curve= 0 ,0
Exp/Cntr=0.3,0.1

Type RM Length L Ch R = 1 ,1990.4  ,188,189.3,190.9
XS GIS Cut Line= 3
     1849483.662      262802.567     1849080.805      263037.849
      1848799.82      263188.497
#Sta/Elev= 30
       0 2043.26    29.8 2026.13    74.4 1999.26   104.2 1979.89     129  1964.4
   168.8 1937.72   238.2 1886.84   243.2 1882.34     268 1851.74     270 1850.03
     273 1847.48   277.9 1847.79     285 1849.43   292.8 1851.16   302.8 1852.47
   387.1 1854.78   451.6  1854.8   491.4 1855.93   516.4 1855.87   571.1 1858.13
   591.1 1862.66     621 1868.15   675.8 1880.36   695.7 1885.05   720.6 1891.67
   730.6  1895.8   735.5 1898.94   750.5 1910.33   770.4 1923.57   785.4 1934.23
#Mann= 3 , 0 , 0
       0      .1       0     270    .045       0     285      .1       0
Bank Sta=270,285
XS Rating Curve= 0 ,0
Exp/Cntr=0.3,0.1

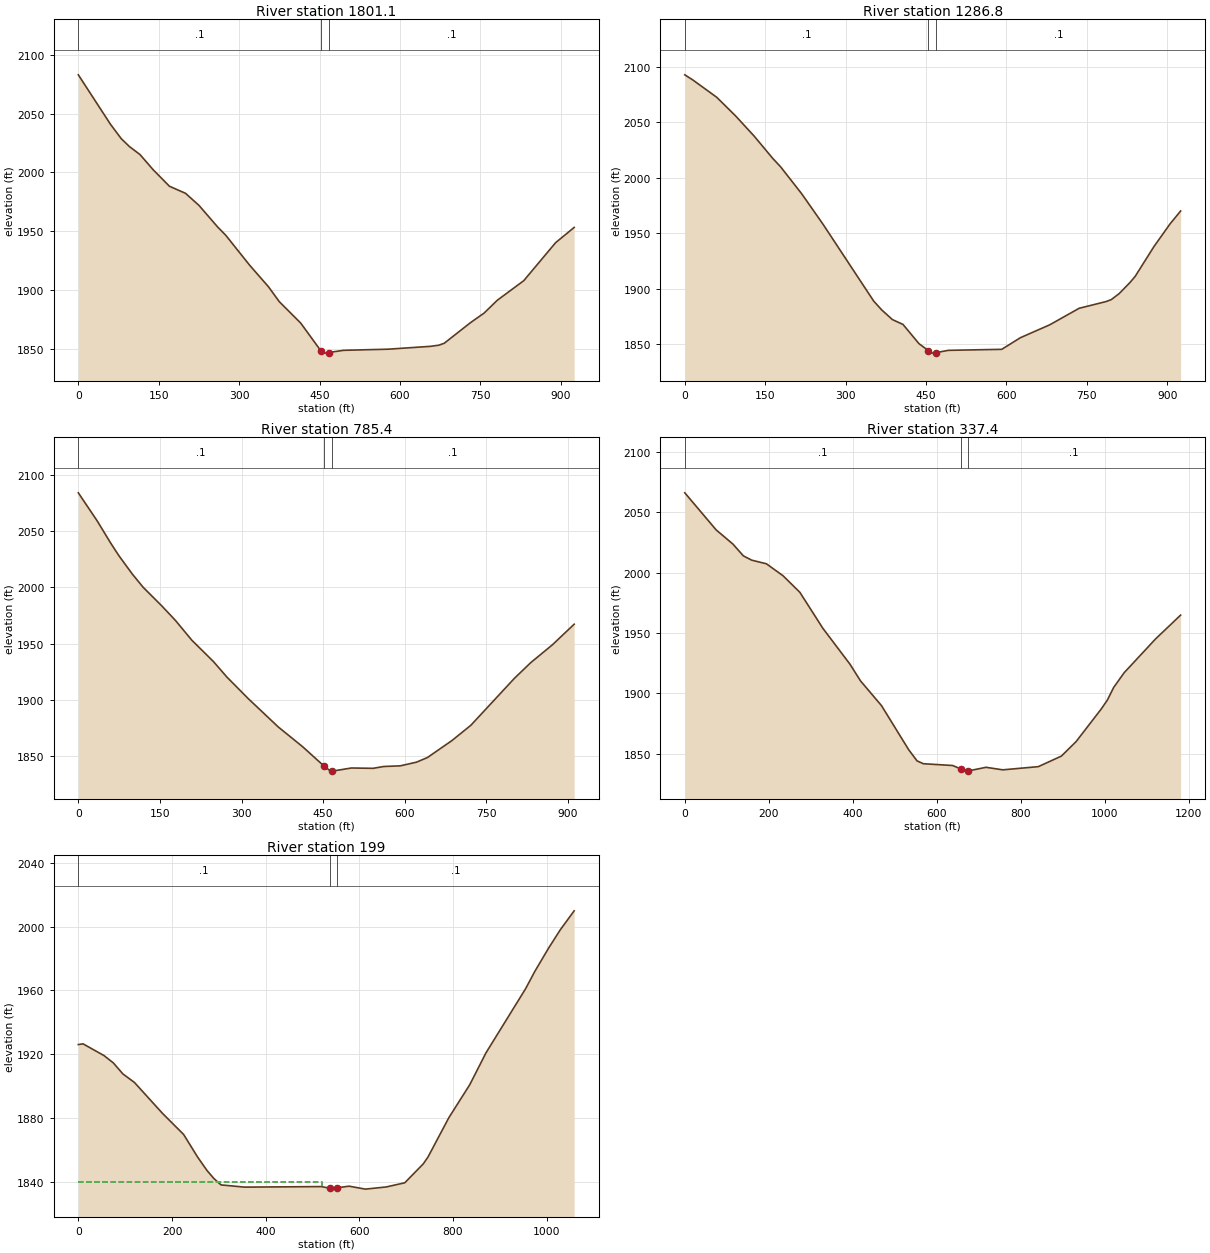
Type RM Length L Ch R = 1 ,1801.1  ,504.7,514.3,522.8
XS GIS Cut Line= 3
     1849570.154      262568.418     1849160.431       262777.07
     1848744.429      262984.943
#Sta/Elev= 30
       0 2082.82      60 2040.86      80 2028.71      95 2022.12     115 2015.21
   139.9 2002.17   169.9 1988.34   199.9 1982.34   224.9 1972.15   259.9 1953.76
   274.9 1946.81   319.8 1921.22   354.8 1903.02   374.8 1890.46   414.8 1872.28
   452.3 1848.85   454.8  1847.5   459.8 1846.81   467.3 1847.33   494.4 1849.18
   578.5 1850.16   657.7  1852.6   672.5 1853.55   682.4 1855.16   731.9 1872.81
   756.6 1880.68   781.4 1891.63   830.8 1908.25   890.2 1940.48   924.8  1953.4
#Mann= 3 , 0 , 0
       0      .1       0   452.3    .045       0   467.3      .1       0
Bank Sta=452.3,467.3
XS Rating Curve= 0 ,0
Exp/Cntr=0.3,0.1

Type RM Length L Ch R = 1 ,1286.8  ,504,501.3,499.2
XS GIS Cut Line= 3
     1849559.531      262308.101      1849107.75      262308.101
     1848635.738      262342.125
#Sta/Elev= 30
       0 2092.94    14.9 2088.34    59.6 2072.68    94.3 2056.12   129.1 2037.85
   163.8 2017.73   178.7 2010.01   218.4 1985.47   258.2 1957.96   352.5 1888.83
   367.4 1880.89   387.2 1872.24   407.1 1867.82   436.9 1850.48   454.4 1844.25
   461.7 1841.95   469.4 1842.48   491.6 1844.46   591.3 1845.37   626.1 1855.86
   680.9  1867.5   735.7  1882.4   785.5  1888.4   795.5 1890.18   810.4 1895.64
   830.4 1905.56   840.3 1911.23   875.2 1938.01   905.1 1958.39     925 1970.13
#Mann= 3 , 0 , 0
       0      .1       0   454.4    .045       0   469.4      .1       0
Bank Sta=454.4,469.4
XS Rating Curve= 0 ,0
Exp/Cntr=0.3,0.1

Type RM Length L Ch R = 1 ,785.4   ,457.9,448.1,438.7
XS GIS Cut Line= 3
     1849450.298      261764.081     1848998.289      261831.289
     1848550.295      261907.784
#Sta/Elev= 30
       0 2084.28    34.8 2059.19    59.6 2039.42    74.5 2028.34    99.3 2011.89
   119.2 2000.13     154 1983.28   178.8 1970.48   208.6 1953.05   248.4 1933.98
   273.2 1920.14   312.9 1900.74   367.6 1875.72   412.3 1858.17   451.6 1840.95
     462 1837.09   466.6 1836.45     467  1836.4   501.9 1839.19   541.9  1838.9
   561.9 1840.55   591.8  1841.1   621.8  1844.4   641.8 1848.51   686.7 1863.58
   721.7 1877.28   801.6 1919.02   831.6    1933   871.5 1948.91   911.5 1967.26
#Mann= 3 , 0 , 0
       0      .1       0   451.6    .045       0   466.6      .1       0
Bank Sta=451.6,466.6
XS Rating Curve= 0 ,0
Exp/Cntr=0.3,0.1

Type RM Length L Ch R = 1 ,337.4   ,135,138.3,141.7
XS GIS Cut Line= 3
     1849614.101      261459.582     1849009.828      261358.293
     1848535.947      261671.072
#Sta/Elev= 30
       0 2066.28    74.7 2035.55   114.6  2023.8   139.5 2014.02   159.4 2010.47
   194.3 2007.48   234.1 1997.51     274 1983.82   328.8 1953.96   393.5 1924.16
   418.4 1910.41   468.2 1889.98     533 1853.42   552.9 1844.16   567.9 1841.78
   637.6  1840.3   658.2 1837.34   672.5 1835.64   673.2  1835.7   717.3 1838.82
   757.1 1836.71   841.8 1839.36   896.6  1848.1   931.5 1860.05   991.2    1887
  1006.2  1894.6  1021.1 1904.99    1046 1917.16  1120.7 1945.16  1180.5 1964.95
#Mann= 3 , 0 , 0
       0      .1       0   658.2    .045       0   673.2      .1       0
Bank Sta=658.2,673.2
XS Rating Curve= 0 ,0
Exp/Cntr=0.3,0.1

Type RM Length L Ch R = 1 ,199     ,217.1,199,180.9
XS GIS Cut Line= 4
     1849421.033      261270.694     1848999.556      261219.914
     1848852.293      261291.006     1848486.675      261587.225
#Sta/Elev= 30
       0    1926      10 1926.46    54.9 1919.08    74.9 1914.46    94.9 1907.64
   119.9 1902.21   179.8 1882.81   224.8 1869.61   254.7 1855.43   274.7 1847.02
   289.7 1841.89   304.7 1837.97   354.6 1836.58   518.7 1836.91     537  1835.9
     552 1836.15   578.1 1837.17   612.8 1835.32   657.4 1836.68     697  1839.3
   736.6 1851.22   746.6 1855.49   791.1 1880.15   835.7 1900.82   870.4 1920.84
   954.6 1960.86   974.4 1971.78  1004.1 1986.54  1028.9 1997.95  1058.6 2009.89
#Mann= 3 , 0 , 0
       0      .1       0     537    .045       0     552      .1       0
#XS Ineff= 2 , 0
          519.45 1840.03
Permanent Ineff=
       F       F
Bank Sta=537,552
XS Rating Curve= 0 ,0
Exp/Cntr=0.3,0.1

Chan Stop Cuts=-1
Use User Specified Reach Order=0